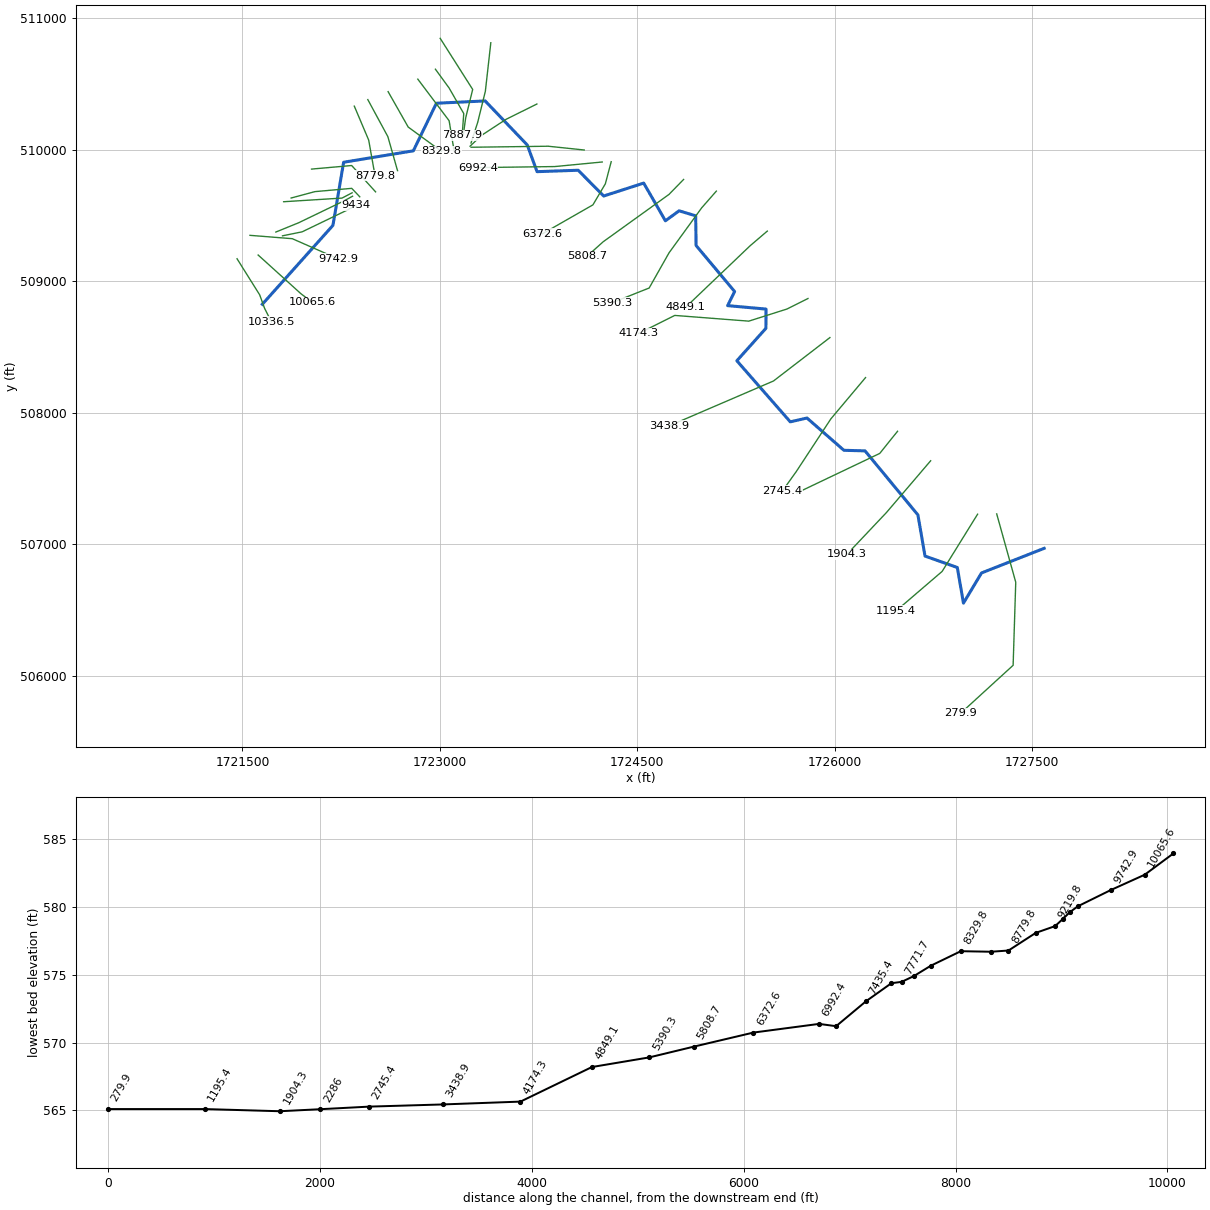
--- TCKTCK.prj (project) ---

Proj Title=TCKTCK
Current Plan=p01
Default Exp/Contr=0,0
English Units
Geom File=g01
Flow File=f01
Plan File=p01
BEGIN DESCRIPTION:
END DESCRIPTION:
DSS Export Rating Curves= 0
DSS Export Rating Curve Sorted= 0
DSS Export Volume Flow Curves= 0
DXF OffsetX= 0
DXF OffsetY= 0
DXF ScaleX= 0
DXF ScaleY= 0

--- TCKTCK.p01 (plan) ---

Plan Title=Floodplain
Program Version=4.00
Geom File=g01
Flow File=f01
K Sum by GR=0
Std Step Tol=0.01
Critical Tol=0.01
Num of Std Step Trials=20
Max Error Tol=0.3
Flow Tol Ratio=0.001
Split Flow NTrial=30
Split Flow Tol=0.02
Split Flow Ratio=0.02
Log Output Level=0
Friction Slope Method=1
Unsteady Friction Slope Method=2
Unsteady Bridges Friction Slope Method=1
Global Log Level=0
CheckData=False
Run HTab=0
Run UNet=0
Run PostProcess=0
UNET Theta=0
UNET Theta Warmup=0
UNET ZTol=0
UNET ZSATol=0
UNET MxIter=0
UNET MaxInSteps=0
UNET DtIC=0
UNET DtMin=0
UNET MaxCRTS=0
UNET WFStab=0
UNET SFStab=0
UNET WFX=0
UNET SFX=0
UNET DSS MLevel=0
UNET DZMax Abort=0
UNET Convert EG Bridges=0
UNET Use Existing IB Tables=0
UNET Froude Limit=0
UNET Froude Power=0
Write IC File=0
Echo Input=False
Echo Output=False
Write Detailed=0

--- TCKTCK.f01 (steady flow) ---

Flow Title=NFF Regression Equation
Program Version=4.10
Number of Profiles= 1
Profile Names=P100yr
River Rch & RM=TCKTCK,Main            ,10336.5
1264.085
River Rch & RM=TCKTCK,Main            ,7771.7
 1370.51
River Rch & RM=TCKTCK,Main            ,3438.9
1458.616
River Rch & RM=TCKTCK,Main            ,279.9
1497.914
Boundary for River Rch & Prof#=TCKTCK,Main            , 1
Up Type= 0
Dn Type= 3
Dn Slope=0.00005
DSS Import GetInterval= 0
DSS Import GetPeak= 0
DSS Import FillOption= 0

--- TCKTCK.g01 (geometry) ---

Geom Title=USGS 10m DEM
Program Version=4.10

River Reach=TCKTCK          ,Main
Reach XY= 30
     1721651.583      508823.922     1722188.136      509423.582
     1722269.431      509903.258      1722799.03      509989.988
     1722974.377      510351.441     1723344.516       510369.15
     1723664.308      510034.775     1723738.961       509831.65
       1724051.2      509842.419     1724245.211       509646.58
     1724549.377      509744.844     1724714.178      509458.304
     1724818.345      509534.259     1724944.169      509496.233
     1724947.294      509270.886     1725239.995      508920.934
     1725187.268      508813.773     1725478.544      508787.552
     1725477.795      508641.382     1725257.016      508394.844
     1725662.919      507930.955     1725790.002      507959.775
     1726070.515      507714.597     1726230.837      507710.303
     1726632.735      507223.733      1726686.66      506910.803
     1726932.088      506824.185      1726978.69      506553.307
     1727115.988      506782.761     1727591.932      506969.812

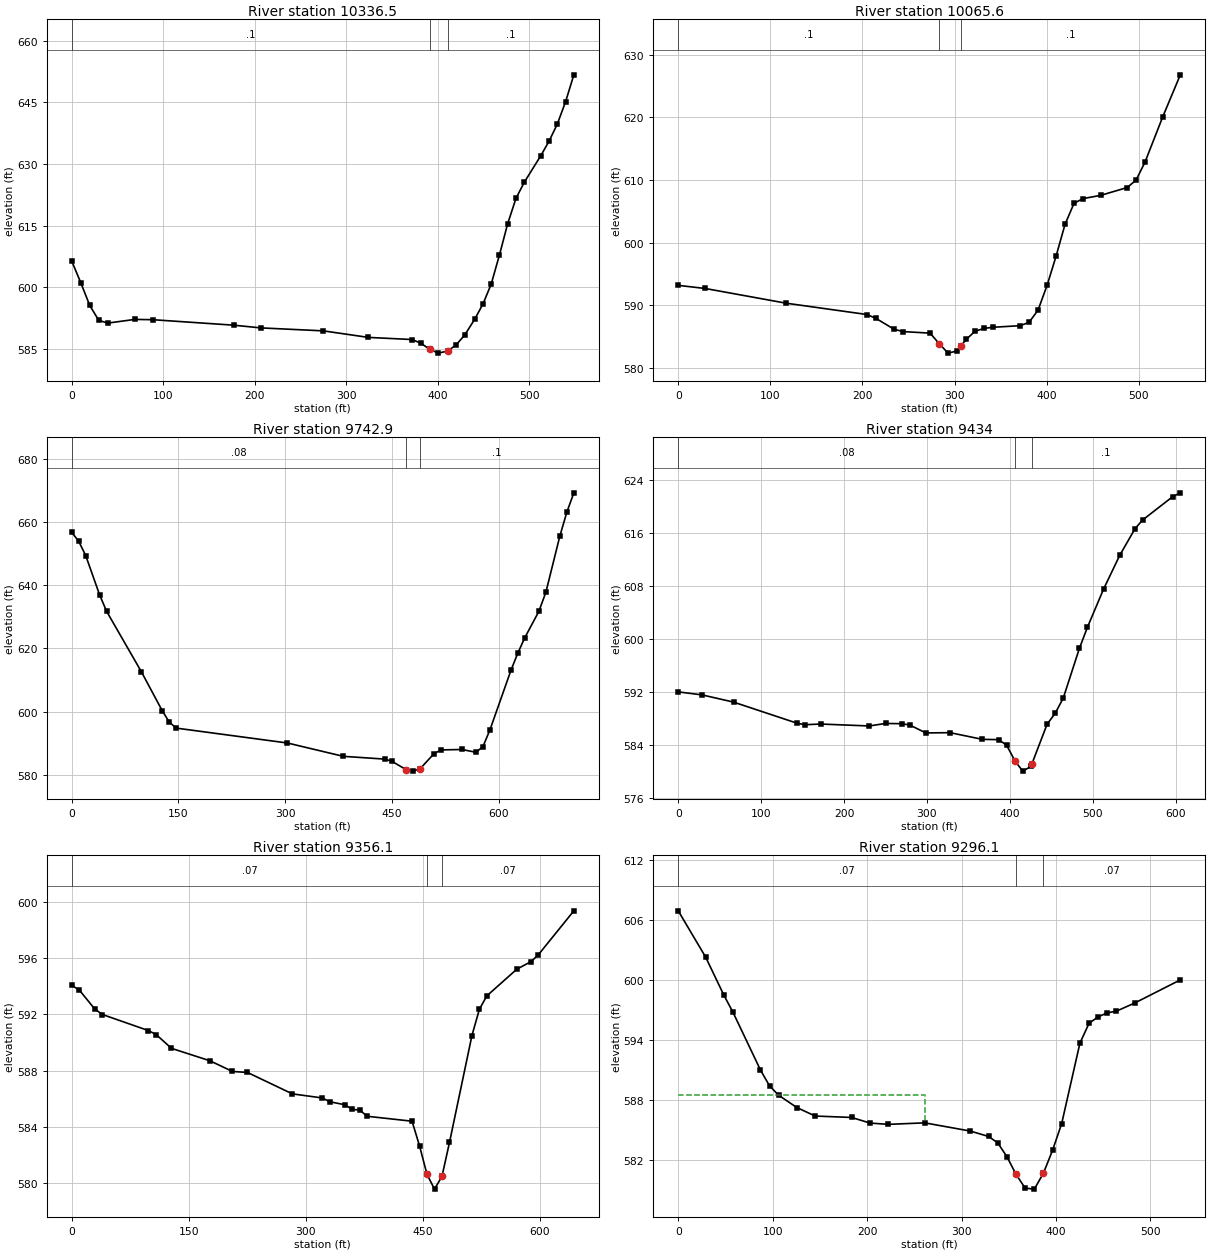
Type RM Length L Ch R = 1 ,10336.5 ,259.1,270.9,282.4
XS GIS Cut Line= 5
     1721459.561      509169.875     1721631.783       508895.43
     1721670.996      508787.629     1721672.107      508786.773
     1721720.996       508690.06
#Sta/Elev= 30
       0  606.35     9.8  601.12    19.6  595.58    29.5  591.93    39.3  591.26
    68.7  592.16    88.4  592.09   176.7  590.76   206.2   590.1   274.9  589.37
     324  587.78   371.8  587.26   381.4  586.36   390.9   584.9   400.5  583.95
   410.6  584.46   419.6  585.89   429.2  588.33   440.1  592.18   449.2   595.9
   458.2  600.76   467.2  607.83   476.2  615.46   485.3  621.65   494.3  625.54
   512.4  632.03   521.4  635.56   530.4  639.71   539.5  645.19   548.5  651.72
#Mann= 3 , 0 , 0
       0      .1       0   390.9    .045       0   410.6      .1       0
Bank Sta=390.9,410.6
XS Rating Curve= 0 ,0
Exp/Cntr=0.3,0.1

Type RM Length L Ch R = 1 ,10065.6 ,315.1,322.6,330.3
XS GIS Cut Line= 3
     1721619.839      509198.283     1721945.881      508903.492
     1722030.256       508839.95
#Sta/Elev= 30
       0   593.2    29.3   592.7   117.2  590.35   205.1  588.54   214.9  587.91
   234.4  586.19   244.2  585.82   273.5  585.57   283.3   583.9     293  582.38
   302.8  582.73   306.6  583.44   312.6  584.56   322.3  585.87   332.1  586.33
   341.9  586.51   371.2  586.76   380.9  587.29   390.7  589.24   400.5  593.19
   410.2  597.81     420  602.93   429.8  606.31   439.6  607.05   458.8  607.57
   487.6  608.82   497.2  610.02   506.8  612.85     526  620.06   545.2  626.81
#Mann= 3 , 0 , 0
       0      .1       0   283.3    .045       0   306.6      .1       0
Bank Sta=283.3,306.6
XS Rating Curve= 0 ,0
Exp/Cntr=0.3,0.1

Type RM Length L Ch R = 1 ,9742.9  ,286.6,309,331.2
XS GIS Cut Line= 3
     1721557.866      509347.902     1721879.524      509322.315
     1722230.088       509168.04
#Sta/Elev= 30
       0  656.69     9.8  653.87    19.6  649.37    39.1  636.97    48.9  631.77
    97.8  612.66   127.1  600.35   136.9  596.78   146.7  594.84   303.1  590.13
   381.6  585.92   440.5  585.03   450.3   584.3     470   581.7   479.8  581.24
   489.6  581.98   509.3   586.8   519.1  587.94   548.6  588.08   568.2  587.18
     578  589.02   587.8   594.3   617.3   613.1   627.1  618.63   636.9  623.47
   656.6  631.77   666.4   637.8     686  655.51   695.9  663.12   705.7   669.2
#Mann= 3 , 0 , 0
       0     .08       0     470    .045       0   489.6      .1       0
Bank Sta=470,489.6
XS Rating Curve= 0 ,0
Exp/Cntr=0.3,0.1

Type RM Length L Ch R = 1 ,9434    ,78.1,77.9,78.1
XS GIS Cut Line= 4
     1721804.864       509344.13     1721954.285      509374.568
     1722296.644      509539.695     1722360.786      509574.684
#Sta/Elev= 30
       0     592    28.6  591.55    66.7  590.46     143  587.29   152.5  587.05
     172  587.15   230.5  586.86     250  587.24   269.4   587.2   279.2  587.01
   298.7  585.81   327.9  585.85   366.9  584.84   386.4   584.8   396.1  583.96
   406.3  581.55   415.6  580.05   425.4  580.76   426.3  581.05   444.9  587.12
   454.6  588.76   464.4  591.06   483.9  598.57   493.6  601.76   513.1  607.52
   532.6  612.61   550.9   616.6     560  617.91   596.5  621.45   605.6  622.02
#Mann= 3 , 0 , 0
       0     .08       0   406.3    .045       0   426.3      .1       0
Bank Sta=406.3,426.3
XS Rating Curve= 0 ,0
Exp/Cntr=0.3,0.1

Type RM Length L Ch R = 1 ,9356.1  ,69.8,59.9,49.9
XS GIS Cut Line= 4
     1721754.394      509372.902     1721927.529      509443.334
     1722273.311      509610.112     1722337.452      509645.101
#Sta/Elev= 30
       0  594.06     9.8  593.72    29.5  592.38    39.4  591.99    98.4  590.85
   108.2  590.57   127.9  589.59   177.1  588.71   206.1  587.95   225.3  587.88
   282.9  586.36   321.3  586.07   330.9   585.8   350.1  585.59   359.7  585.26
   369.3  585.21   378.9  584.77   436.4  584.42     446  582.67   455.6  580.64
   465.2   579.6   474.8  580.51   484.4  582.91   513.2   590.5   522.8  592.37
   532.4  593.32   570.8  595.21   589.1  595.75   598.2  596.22   643.9  599.35
#Mann= 3 , 0 , 0
       0     .07       0   455.6    .045       0   474.8     .07       0
Bank Sta=455.6,474.8
XS Rating Curve= 0 ,0
Exp/Cntr=0.3,0.1

Type RM Length L Ch R = 1 ,9296.1  ,73.1,76.4,77.9
XS GIS Cut Line= 3
     1721813.474      509603.145     1722257.224      509630.922
     1722334.307        509671.2
#Sta/Elev= 30
       0  606.94      29  602.32    48.3  598.52      58   596.8      87  591.05
    96.7  589.45   106.3  588.52   125.6  587.29     145  586.44   183.6   586.3
     203  585.74   222.3  585.61     261  585.76   309.3  584.94   328.6   584.4
   338.3  583.76     348  582.38   357.6  580.63   367.3  579.24     377  579.14
   386.6  580.72   396.3  583.01     406  585.69   425.3  593.72     435  595.71
   444.6  596.35   454.3  596.75     464  596.92   483.3  597.73   531.6  600.04
#Mann= 3 , 0 , 0
       0     .07       0   357.6    .045       0   386.6     .07       0
#XS Ineff= 2 , 0
          260.99  588.58
Permanent Ineff=
       F       F
Bank Sta=357.6,386.6
XS Rating Curve= 0 ,0
Exp/Cntr=0.3,0.1

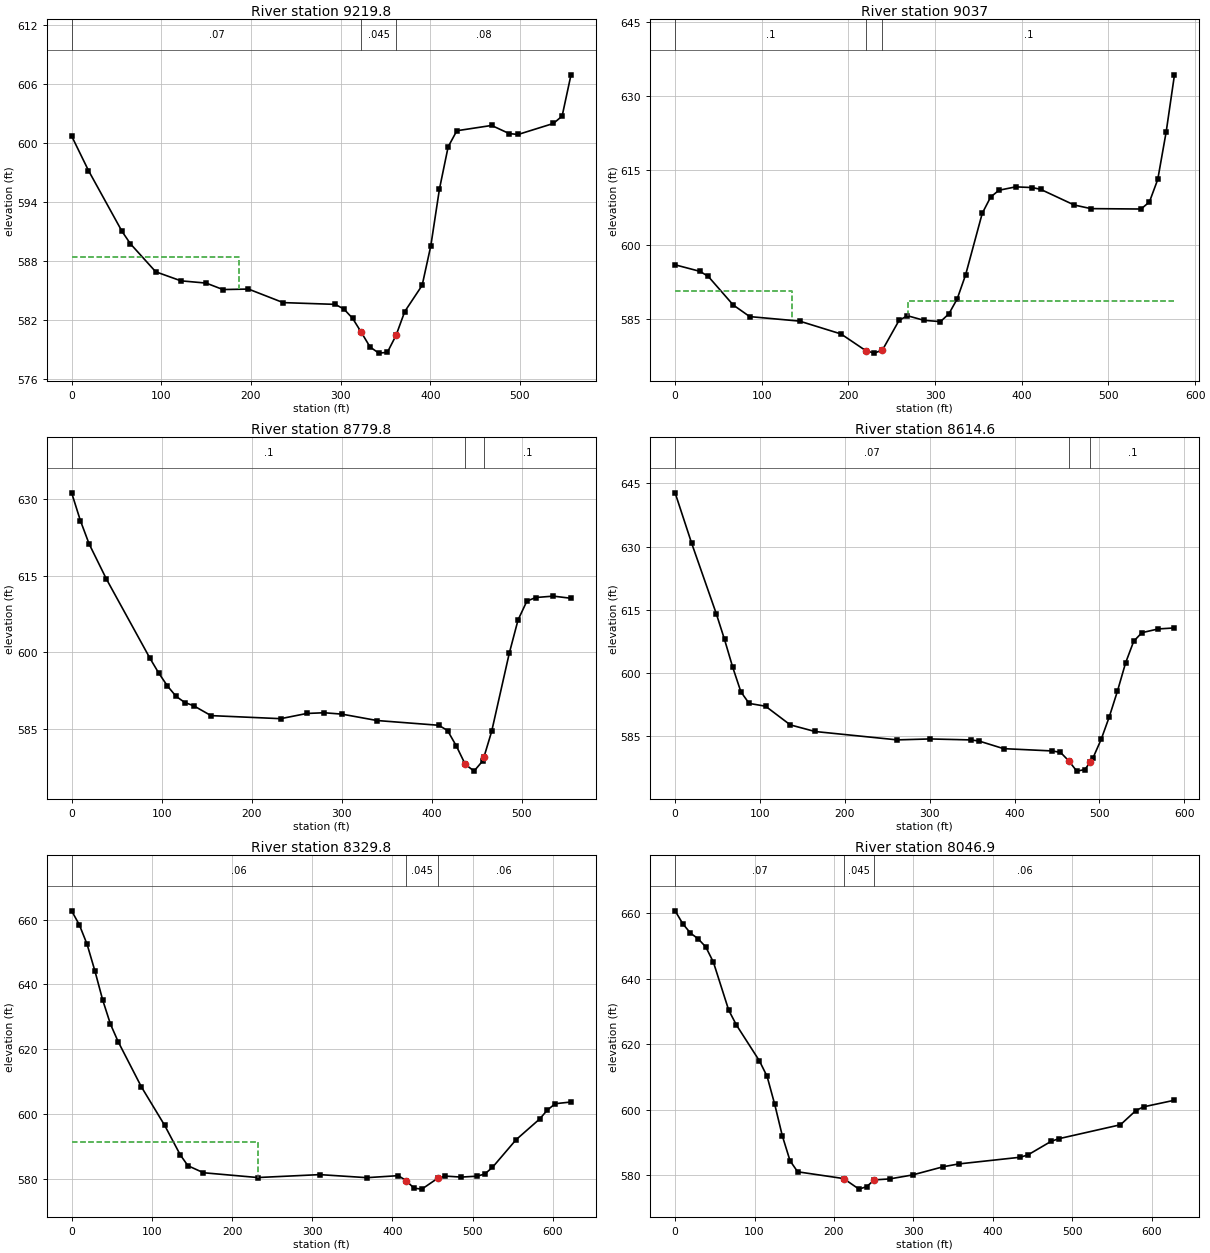
Type RM Length L Ch R = 1 ,9219.8  ,185.4,182.7,227.5
XS GIS Cut Line= 4
     1721870.192      509631.304     1722051.276      509679.948
     1722331.023      509704.882     1722391.946      509640.645
#Sta/Elev= 30
       0  600.72    18.8   597.2    56.2     591    65.6  589.73    93.8  586.88
   121.9  585.96     150  585.73   168.8  585.07   197.2  585.12   235.9  583.74
     294  583.56   303.7  583.08   313.4  582.13   323.1   580.7   332.8  579.22
   342.5  578.59   352.1  578.67   361.8   580.4   371.5  582.83   390.9   585.5
   400.6  589.55   410.2  595.32   419.9  599.62   429.6  601.26   468.4   601.8
     488  600.97   497.9  600.88   537.2     602     547  602.75   556.9  606.96
#Mann= 3 , 0 , 0
       0     .07       0   323.1    .045       0   361.8     .08       0
#XS Ineff= 2 , 0
          186.26  588.44
Permanent Ineff=
       F       F
Bank Sta=323.1,361.8
XS Rating Curve= 0 ,0
Exp/Cntr=0.3,0.1

Type RM Length L Ch R = 1 ,9037    ,294.9,257.3,172.1
XS GIS Cut Line= 3
      1722025.58      509851.165     1722330.602      509878.352
     1722511.947      509678.328
#Sta/Elev= 30
       0  595.91    28.7  594.59    38.3  593.56      67  587.81    86.1  585.46
   143.6  584.55   191.4  581.96   220.1  578.58   229.7  578.09   239.2  578.71
   258.4  584.69     268  585.64   287.1  584.71   306.2  584.45   315.9  586.02
   325.5  589.04   335.2  593.89   354.4  606.31   364.1  609.59   373.7  610.96
     393  611.64   412.3   611.5   421.9  611.13   460.5  607.98   479.8  607.25
   537.6  607.17   547.3   608.6   556.9  613.14   566.6  622.71   576.2  634.25
#Mann= 3 , 0 , 0
       0      .1       0   220.1    .045       0   239.2      .1       0
#XS Ineff= 2 , 0
          134.62  590.69  268.68          588.56
Permanent Ineff=
       F       F
Bank Sta=220.1,239.2
XS Rating Curve= 0 ,0
Exp/Cntr=0.3,0.1

Type RM Length L Ch R = 1 ,8779.8  ,162.6,165.1,167.6
XS GIS Cut Line= 3
     1722350.553       510329.46     1722459.928      510071.126
     1722507.844      509801.335
#Sta/Elev= 30
       0  631.18     9.7  625.76    19.4   621.2    38.7   614.3    87.1  598.81
    96.7  595.97   106.4  593.43   116.1  591.39   125.8  590.19   135.4  589.58
   154.8  587.64   232.2  587.04   261.2  588.06   280.5   588.2   300.1  587.93
   339.2  586.68   407.8  585.75   417.5  584.72   427.3  581.69   437.1  578.14
   446.9  576.79   456.7  578.82   457.9  579.52   466.5  584.56     486  599.79
   495.8  606.34   505.6  610.01   515.4  610.72     535  610.99   554.6  610.57
#Mann= 3 , 0 , 0
       0      .1       0   437.1    .045       0   457.9      .1       0
Bank Sta=437.1,457.9
XS Rating Curve= 0 ,0
Exp/Cntr=0.3,0.1

Type RM Length L Ch R = 1 ,8614.6  ,267.4,284.8,301.4
XS GIS Cut Line= 3
     1722453.157      510379.112     1722605.414      510097.862
     1722678.851      509839.529
#Sta/Elev= 30
       0  642.78    19.4  630.86    48.5  614.09    58.2  607.97    67.8  601.41
    77.5  595.53    87.2  592.78   106.6  592.11   135.7  587.68   164.8  586.11
   261.7  584.12   300.4  584.34   348.6  584.11   358.2  583.84     387  582.04
   444.5  581.49   454.1  581.15   463.7  579.17   473.3   576.7   482.9  577.07
   489.4  578.97   492.5  579.88   502.1  584.28   511.6   589.6   521.2  595.69
   530.8   602.4   540.4  607.55     550  609.57   569.2  610.46   588.4   610.7
#Mann= 3 , 0 , 0
       0     .07       0   463.7    .045       0   489.4      .1       0
Bank Sta=463.7,489.4
XS Rating Curve= 0 ,0
Exp/Cntr=0.3,0.1

Type RM Length L Ch R = 1 ,8329.8  ,290.3,282.9,275.2
XS GIS Cut Line= 3
     1722607.323      510439.529     1722760.101      510170.432
     1723013.053       509985.71
#Sta/Elev= 30
       0   662.7     9.7  658.33    19.3  652.34      29  644.15    38.7  635.18
    48.4  627.71      58  622.29      87  608.32     116  596.44   135.4  587.35
     145  583.97   164.4   581.8   232.1  580.32   309.4  581.22   368.2  580.28
   407.3   580.9   417.1  579.39   426.9  577.03   436.7  576.74   456.3  580.06
     466  580.77   485.6  580.46   505.2  580.73     515  581.38   524.8  583.47
   554.2     592   583.5  598.37   593.3  601.18   603.1  603.13   622.7  603.65
#Mann= 3 , 0 , 0
       0     .06       0   417.1    .045       0   456.3     .06       0
#XS Ineff= 2 , 0
          232.05  591.33
Permanent Ineff=
       F       F
Bank Sta=417.1,456.3
XS Rating Curve= 0 ,0
Exp/Cntr=0.3,0.1

Type RM Length L Ch R = 1 ,8046.9  ,162,159,155.5
XS GIS Cut Line= 3
     1722833.018      510534.552     1723070.865       510218.58
      1723109.06      509988.545
#Sta/Elev= 30
       0  660.79     9.6  656.86    19.3  653.98    28.9  652.25    38.6  649.75
    48.2  645.09    67.5  630.39    77.2  625.86   106.1  614.92   115.8  610.16
   125.4   601.6     135  591.95   144.7  584.34   154.3  580.97   212.2   578.9
   231.5  575.67   241.2  576.43   250.8   578.5   270.1  578.79     299  580.01
   337.6  582.52   356.9  583.37   434.4  585.42   444.1  586.12   473.2  590.26
   482.9  591.08   560.7  595.36   580.1   599.7   589.8  600.84   628.7  602.86
#Mann= 3 , 0 , 0
       0     .07       0   212.2    .045       0   250.8     .06       0
Bank Sta=212.2,250.8
XS Rating Curve= 0 ,0
Exp/Cntr=0.3,0.1

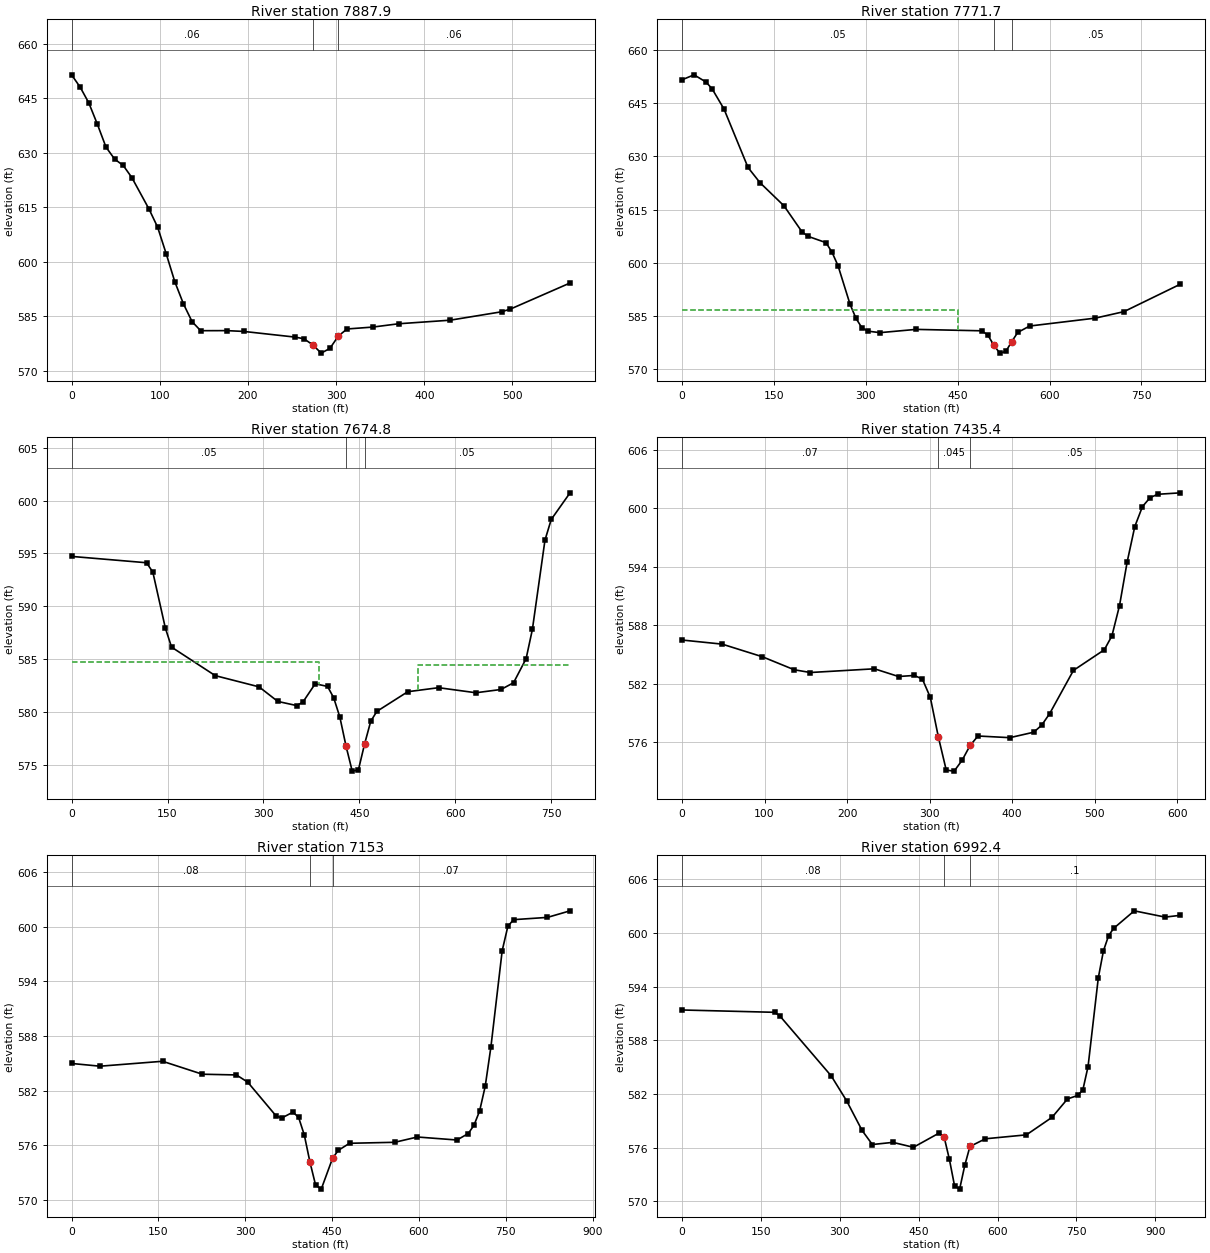
Type RM Length L Ch R = 1 ,7887.9  ,135.2,116.2,96.6
XS GIS Cut Line= 4
     1722966.698      510610.073     1723070.266      510468.131
     1723181.976      510273.267     1723170.092      510108.756
#Sta/Elev= 30
       0  651.46     9.8  648.04    19.5  643.75    29.3  637.84      39  631.58
    48.8  628.28    58.6  626.52    68.3  623.21    87.8  614.54    97.6  609.54
   107.4  602.16   117.1  594.52   126.9  588.43   136.7  583.55   146.4  581.08
   175.7   581.1   195.2  580.88   253.8  579.31   263.6  578.85   273.4  577.21
   283.1  574.91   292.9  576.21   302.7  579.64   312.4  581.55   341.7  582.08
     371  582.99   429.4  583.97   487.6  586.28   497.4     587   565.3   594.2
#Mann= 3 , 0 , 0
       0     .06       0   273.4    .045       0   302.7     .06       0
Bank Sta=273.4,302.7
XS Rating Curve= 0 ,0
Exp/Cntr=0.3,0.1

Type RM Length L Ch R = 1 ,7771.7  ,96.9,96.9,96.9
XS GIS Cut Line= 4
     1723003.018      510844.641     1723249.914      510456.281
     1723196.325       510238.49     1723178.773      510110.492
#Sta/Elev= 30
       0  651.63    19.6  653.03    39.2  650.99      49   649.1    68.5  643.38
   107.7  626.88   127.3  622.58   166.4  616.06   195.8  608.72   205.6  607.45
     235  605.66   244.8  602.97   254.6  599.17   274.2  588.31     284  584.27
   293.7  581.62   303.5  580.68   323.1  580.26   381.9  581.18   489.4  580.78
   499.2  579.58     509   576.7   518.7  574.48   528.5  574.95   538.2  577.71
     548  580.33   567.5  582.13   674.7  584.36   721.4  586.19   813.7  593.96
#Mann= 3 , 0 , 0
       0     .05       0     509    .045       0   538.2     .05       0
#XS Ineff= 2 , 0
          450.55  586.52
Permanent Ineff=
       F       F
Bank Sta=509,538.2
XS Rating Curve= 0 ,0
Exp/Cntr=0.3,0.1

Type RM Length L Ch R = 1 ,7674.8  ,258.2,239.5,219.8
XS GIS Cut Line= 4
      1723387.74      510811.308     1723346.164      510442.392
     1723288.518      510208.113      1723237.28      510049.265
#Sta/Elev= 30
       0  594.71   117.2  594.11     127  593.23   146.6  587.93   156.3  586.12
   224.7  583.42   293.1  582.36   322.4  580.98   351.7  580.59   361.5   580.9
   380.9  582.65   400.2   582.4   409.8  581.33   419.5  579.49   429.2  576.73
   438.8  574.38   448.5   574.5   458.1  576.94   467.8  579.11   477.4  580.04
   525.7   581.9   573.9  582.28   632.2   581.8   671.4  582.11   691.1  582.75
   710.7  585.03   720.5  587.79   740.2  596.25     750  598.21   779.4  600.73
#Mann= 3 , 0 , 0
       0     .05       0   429.2    .045       0   458.1     .05       0
#XS Ineff= 2 , 0
          386.81  584.74  542.12          584.41
Permanent Ineff=
       F       F
Bank Sta=429.2,458.1
XS Rating Curve= 0 ,0
Exp/Cntr=0.3,0.1

Type RM Length L Ch R = 1 ,7435.4  ,296.7,282.3,263.2
XS GIS Cut Line= 4
     1723737.592      510345.515     1723502.592      510228.848
     1723317.141      510107.425     1723229.814      510024.959
#Sta/Elev= 30
       0  586.49    48.6  586.07    97.2  584.78     136  583.44   155.5  583.16
   233.2  583.54   262.4  582.75   281.6  582.86   291.3  582.48   300.9  580.61
   310.6  576.57   320.2  573.15   329.8  573.05   339.5  574.17   349.1  575.68
   358.7  576.65   397.3  576.48   426.2  577.04   435.8  577.75   445.5  578.94
   474.4  583.38   511.8  585.49     521  586.92   530.2  590.02   539.5  594.51
   548.7  598.12     558  600.17   567.2  601.08   576.4  601.43   604.1  601.58
#Mann= 3 , 0 , 0
       0     .07       0   310.6    .045       0   349.1     .05       0
Bank Sta=310.6,349.1
XS Rating Curve= 0 ,0
Exp/Cntr=0.3,0.1

Type RM Length L Ch R = 1 ,7153    ,359.1,160.6,164.9
XS GIS Cut Line= 3
     1724097.172      509996.259     1723823.734      510024.904
     1723237.797      510017.092
#Sta/Elev= 30
       0     585    49.1   584.7   157.1  585.24   225.8  583.82   284.7  583.74
   304.2  582.95   353.1  579.25   362.8  579.01   382.4  579.66   392.1  579.08
   401.9  577.16   411.7  574.17   421.4  571.66   431.2  571.21   450.7  574.59
   460.5  575.46     480  576.24   558.2  576.35   597.2  576.93   665.6   576.6
   685.1  577.31   694.9  578.21   704.7  579.78   714.4   582.5   724.2   586.8
   743.7  597.38   753.5  600.05   763.3  600.78   821.9  601.03   860.9  601.75
#Mann= 3 , 0 , 0
       0     .08       0   411.7    .045       0   450.7     .07       0
Bank Sta=411.7,450.7
XS Rating Curve= 0 ,0
Exp/Cntr=0.3,0.1

Type RM Length L Ch R = 1 ,6992.4  ,394.9,619.8,646.1
XS GIS Cut Line= 3
     1724234.324      509905.113     1723874.081      509870.391
     1723288.144      509862.578
#Sta/Elev= 30
       0  591.38   176.1  591.12   185.8  590.73   283.7  584.02     313  581.24
   342.4  577.93   361.9  576.36     401   576.6     440  576.05   488.9  577.64
   498.6  577.15   508.4  574.71   518.2  571.76   527.9  571.38   537.7  574.04
   547.5  576.14   576.8     577   654.9  577.44   703.7   579.4     733  581.45
   752.6  581.84   762.3  582.48   772.1  585.06   791.6  594.97   801.4  597.99
   811.2  599.68   820.9   600.5     860  602.45   918.6  601.75   947.9  601.95
#Mann= 3 , 0 , 0
       0     .08       0   498.6    .045       0   547.5      .1       0
Bank Sta=498.6,547.5
XS Rating Curve= 0 ,0
Exp/Cntr=0.3,0.1

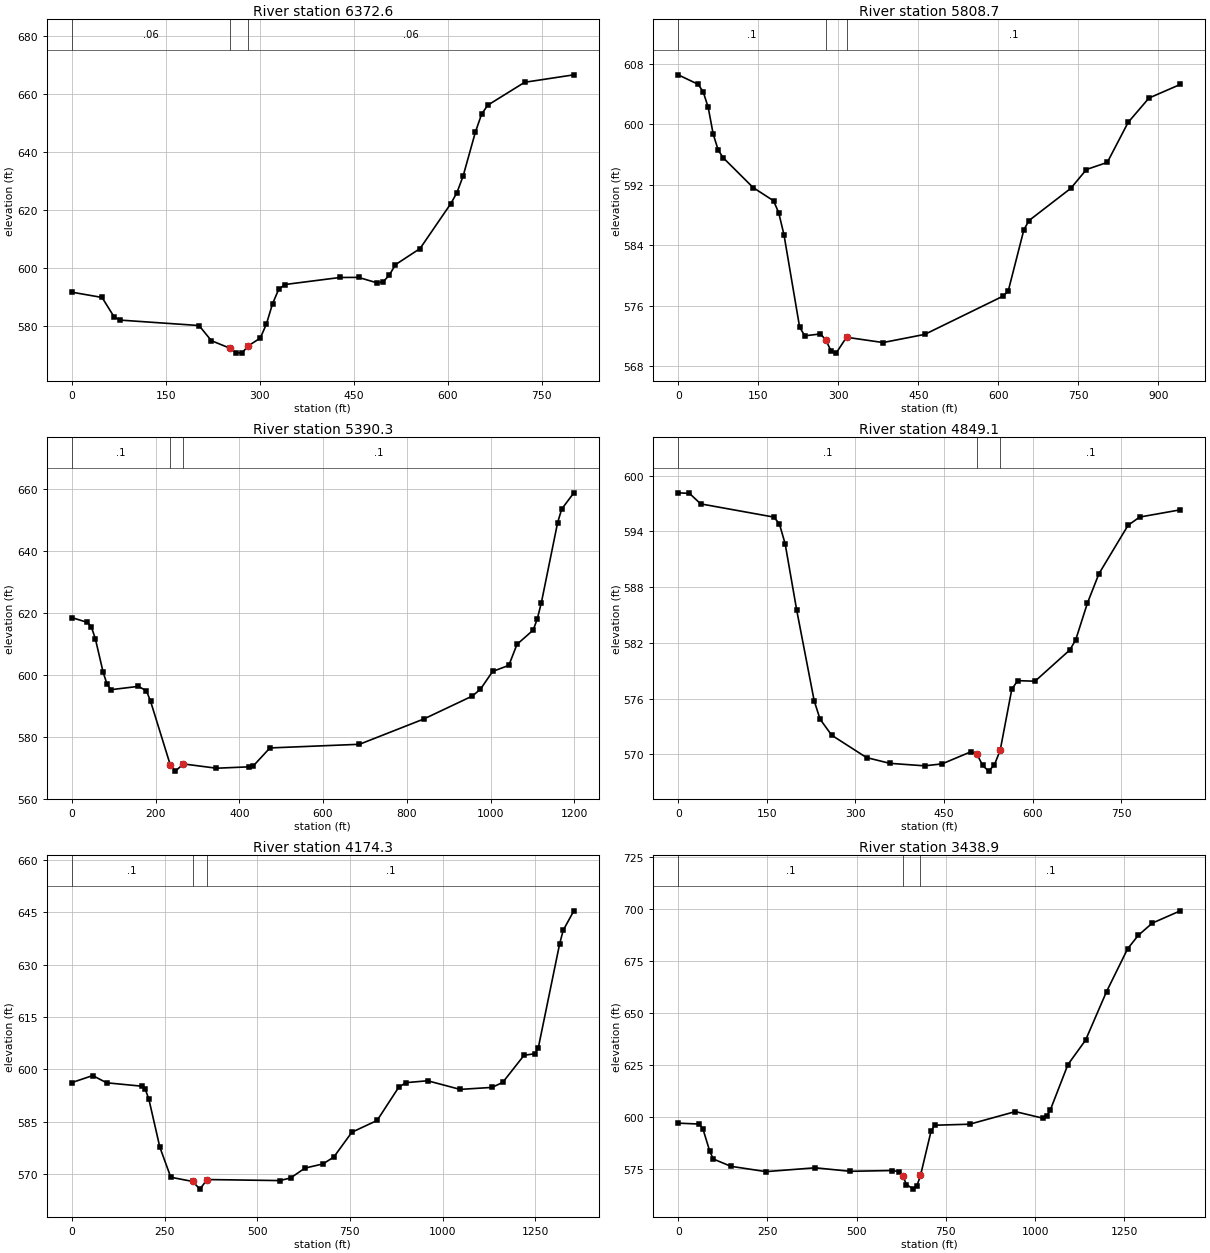
Type RM Length L Ch R = 1 ,6372.6  ,575,563.9,549.1
XS GIS Cut Line= 4
     1724302.314      509907.181      1724257.87      509739.126
     1724163.425      509579.404     1723780.092      509359.959
#Sta/Elev= 30
       0  591.73    48.3  589.91    67.6   583.2    77.3  582.11   203.1  580.24
   222.7  575.03     252  572.46   261.7  570.94   271.5  570.74   281.3   573.2
   300.8  575.92   310.6  580.78   320.3  587.71   330.1  592.68   339.9  594.36
   428.1  596.79   457.5  596.82     487  594.94   496.8  595.29   506.6  597.56
   516.4  601.19   555.7  606.75   604.8  622.22   614.6  626.02   624.4  631.69
     644  646.84   653.9  653.02   663.7  656.11   722.6     664   801.1  666.57
#Mann= 3 , 0 , 0
       0     .06       0     252    .045       0   281.3     .06       0
Bank Sta=252,281.3
XS Rating Curve= 0 ,0
Exp/Cntr=0.3,0.1

Type RM Length L Ch R = 1 ,5808.7  ,407.3,418.4,427.9
XS GIS Cut Line= 4
     1724852.314      509772.459     1724741.203       509658.57
     1724241.203      509298.848     1724117.592      509187.737
#Sta/Elev= 30
       0  606.53    37.4  605.27    46.8  604.28    56.2  602.21    65.5   598.7
    74.9  596.57    84.2  595.56   140.4  591.61   178.7  589.86   188.4  588.27
   198.2  585.38   227.6  573.13   237.3  571.99   266.7  572.24   276.4  571.46
   286.2  570.04     296   569.7   315.5   571.8     384   571.1   462.2  572.18
   608.9  577.24   618.6   577.9     648  586.02   657.7  587.25     736  591.51
   765.3     594   804.4  594.94   843.5  600.24   882.6  603.46   941.3  605.26
#Mann= 3 , 0 , 0
       0      .1       0   276.4    .045       0   315.5      .1       0
Bank Sta=276.4,315.5
XS Rating Curve= 0 ,0
Exp/Cntr=0.3,0.1

Type RM Length L Ch R = 1 ,5390.3  ,545.1,541.1,536
XS GIS Cut Line= 5
     1725101.157      509683.779     1724990.046      509557.043
     1724741.782      509215.029      1724590.74      508947.668
     1724311.226      508836.556
#Sta/Elev= 30
       0  618.51    37.4  616.95    46.8  615.47    56.2  611.73    74.9  600.85
    84.3  596.97    93.6  595.22   159.2  596.29   178.4  594.83   188.2  591.46
     235  571.02   247.2  568.91   266.8  571.23   345.5  569.85   424.1   570.3
   433.9  570.65   473.2   576.4   687.1  577.58   840.7  585.75   956.5  593.16
   975.9  595.36    1005  601.11  1043.8  603.08  1063.2  609.86    1102  614.48
  1111.7   618.1  1121.4  623.31  1160.2  649.15  1169.9  653.54    1199  658.81
#Mann= 3 , 0 , 0
       0      .1       0     235    .045       0   266.8      .1       0
Bank Sta=235,266.8
XS Rating Curve= 0 ,0
Exp/Cntr=0.3,0.1

Type RM Length L Ch R = 1 ,4849.1  ,684.9,674.8,661
XS GIS Cut Line= 3
      1725488.31      509379.959     1725358.101      509268.848
     1724866.782      508800.098
#Sta/Elev= 30
       0  598.16      19   598.1      38  596.97   161.7  595.55   171.2  594.84
     181  592.68   200.7   585.5   230.2  575.77   240.1   573.8   259.8  572.07
   318.8  569.66   358.2  569.04   417.2  568.77   446.7  568.98   495.9  570.29
   505.8  570.02   515.6  568.81   525.5   568.2   535.3  568.86   545.2  570.45
   564.8     577   574.7  577.94   604.2  577.88   663.2  581.25   673.1  582.34
   692.8  586.27   712.4  589.45   761.7  594.66   781.3  595.55   850.2  596.33
#Mann= 3 , 0 , 0
       0      .1       0   505.8    .045       0   545.2      .1       0
Bank Sta=505.8,545.2
XS Rating Curve= 0 ,0
Exp/Cntr=0.3,0.1

Type RM Length L Ch R = 1 ,4174.3  ,731.9,735.4,736.5
XS GIS Cut Line= 5
     1725797.337      508867.806     1725637.615      508787.945
     1725347.685      508695.931     1724785.185      508739.334
     1724510.879      508602.181
#Sta/Elev= 30
       0  596.19    56.4  598.21      94  596.14   188.4  595.17   198.2   594.3
     208  591.37   237.4  577.69   266.9  569.06   325.8  567.85   345.4  565.65
     365   568.4   560.6   568.1   589.8  568.84   628.7  571.68   677.3  572.88
   706.5  574.85   755.1  581.96   823.2  585.34   881.6  594.88     901  596.18
   959.4  596.72  1046.9  594.25  1133.2  594.82  1161.9  596.26  1219.4  604.03
  1248.2  604.47  1257.8  606.19  1315.3  635.98  1324.9  639.87  1353.6  645.45
#Mann= 3 , 0 , 0
       0      .1       0   325.8    .045       0     365      .1       0
Bank Sta=325.8,365
XS Rating Curve= 0 ,0
Exp/Cntr=0.3,0.1

Type RM Length L Ch R = 1 ,3438.9  ,678.7,693.5,705.7
XS GIS Cut Line= 3
     1725964.004      508570.931     1725535.185       508241.07
     1724740.046      507899.056
#Sta/Elev= 30
       0  597.14      59   596.7    68.9  594.51    88.5  583.54    98.4   579.9
   147.6   576.4   245.9  573.85   383.6  575.69     482     574     600  574.38
   619.7  573.78   629.5  571.67   639.4  567.63     659  565.44   668.9  567.17
   678.7  571.99   708.2  593.24   718.1  596.14   816.4  596.63   944.3  602.69
    1023  599.46  1032.8  600.64  1042.6  603.56  1091.8   625.3    1141  636.97
    1200  660.36    1259  680.91  1288.6  687.33  1327.9  693.23  1406.6  699.15
#Mann= 3 , 0 , 0
       0      .1       0   629.5    .045       0   678.7      .1       0
Bank Sta=629.5,678.7
XS Rating Curve= 0 ,0
Exp/Cntr=0.3,0.1

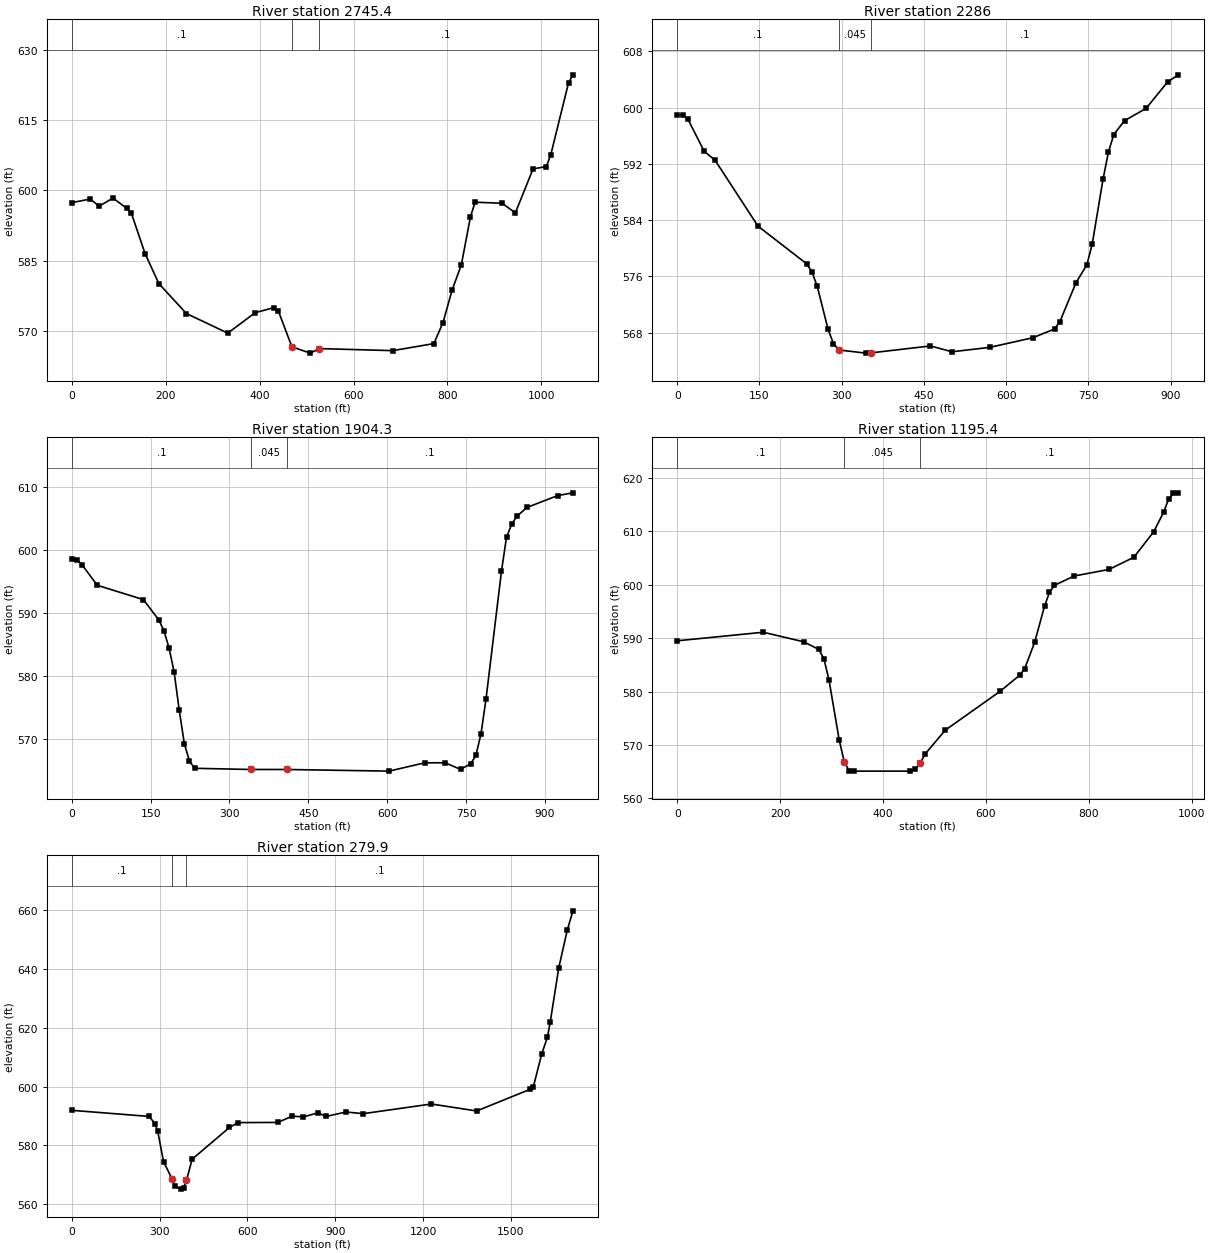
Type RM Length L Ch R = 1 ,2745.4  ,471.8,459.4,445.1
XS GIS Cut Line= 4
     1726234.837      508267.112     1725970.948      507952.876
     1725708.796       507553.57     1725604.629      507407.737
#Sta/Elev= 30
       0   597.4    39.1  598.16    58.6  596.66    87.9  598.37   117.2  596.18
     127  595.15   156.3  586.49   185.6   580.1   244.2  573.73   332.2  569.55
   390.8  573.92   429.8  574.97   439.6  574.37   468.8  566.63   507.8  565.28
   527.3  566.25   683.3  565.81     771  567.31   790.5   571.8     810  578.78
   829.5  584.09     849  594.38   858.8  597.49   916.3  597.27   944.6  595.22
   982.3   604.6  1010.6   605.1  1020.1  607.66  1057.8  622.97  1067.2  624.68
#Mann= 3 , 0 , 0
       0      .1       0   468.8    .045       0   527.3      .1       0
Bank Sta=468.8,527.3
XS Rating Curve= 0 ,0
Exp/Cntr=0.3,0.1

Type RM Length L Ch R = 1 ,2286    ,371.4,381.7,392.3
XS GIS Cut Line= 3
     1726477.893      507859.126     1726342.476      507690.723
     1725712.268      507390.376
#Sta/Elev= 30
       0  598.93     9.8  598.96    19.6  598.32    49.1  593.78    68.8  592.53
   147.3  583.14   235.8   577.8   245.6  576.66   255.4  574.57   275.1  568.47
   284.9  566.45   294.8  565.54   343.9  565.09   353.8  565.13   461.9  566.11
   501.2  565.28   570.1  565.91   648.7  567.28   688.1  568.52   697.9  569.56
   727.4  575.12   747.1  577.64   756.9  580.59   776.6  589.81   786.4  593.65
   796.2  596.16   815.9  598.14   855.2  599.88   894.6  603.66   914.2  604.65
#Mann= 3 , 0 , 0
       0      .1       0   294.8    .045       0   353.8      .1       0
Bank Sta=294.8,353.8
XS Rating Curve= 0 ,0
Exp/Cntr=0.3,0.1

Type RM Length L Ch R = 1 ,1904.3  ,704.9,708.9,712.5
XS GIS Cut Line= 3
     1726729.629      507635.168      1726394.56      507242.806
     1726094.212      506925.098
#Sta/Elev= 30
       0  598.55     9.7  598.41    19.5  597.63    48.7  594.37   136.3  592.11
   165.5   588.9   175.2  587.21     185  584.48   194.7  580.67   204.4  574.62
   214.2  569.27   223.9  566.54   233.6  565.39   340.7   565.2   408.9   565.2
   603.4  564.94   671.4  566.26   710.3  566.26   739.4  565.22   758.8  566.11
   768.6  567.42   778.3  570.83     788  576.42   817.2  596.56   826.9  602.01
   836.6  604.02   846.3  605.29   865.7   606.7     924  608.58   953.2  609.02
#Mann= 3 , 0 , 0
       0      .1       0   340.7    .045       0   408.9      .1       0
Bank Sta=340.7,408.9
XS Rating Curve= 0 ,0
Exp/Cntr=0.3,0.1

Type RM Length L Ch R = 1 ,1195.4  ,893.3,915.5,936.3
XS GIS Cut Line= 3
     1727086.226      507229.265     1726816.782      506794.543
     1726465.393      506493.154
#Sta/Elev= 30
       0   589.5   167.2   591.1   245.9  589.31   275.4  587.87   285.2  586.11
   295.1  582.12   314.7     571   324.6  566.87   334.4  565.14   344.2   565.1
   452.4   565.1   462.3  565.41   472.1  566.55     482  568.33   521.1  572.77
   627.2  580.01   665.8  583.06   675.4  584.28   694.7  589.19     714  595.97
   723.6  598.57   733.3  599.89   771.8  601.63   839.4  602.86   887.6  605.13
   926.2   609.9   945.4  613.55   955.1  616.01   964.7   617.1   974.4   617.2
#Mann= 3 , 0 , 0
       0      .1       0   324.6    .045       0   472.1      .1       0
Bank Sta=324.6,472.1
XS Rating Curve= 0 ,0
Exp/Cntr=0.3,0.1

Type RM Length L Ch R = 1 ,279.9   ,277.8,279.9,282
XS GIS Cut Line= 4
     1727231.346      507231.322     1727376.027      506712.279
     1727356.134      506081.107     1726956.452      505715.788
#Sta/Elev= 30
       0  591.93   264.5  589.85   284.1  587.42   293.9  584.73   313.5  574.47
   342.9  568.55   352.7  566.02   372.3   565.1   382.1  565.59   391.9  568.15
   411.5  575.32   538.8   586.1     568  587.75     704  587.81   752.6  589.94
   791.4   589.7     840  591.05   869.2  589.87   937.2  591.36   995.4  590.79
  1228.3  594.08    1383  591.71  1566.8  599.14  1576.4  599.88  1605.4   611.2
  1624.8  616.87  1634.4  622.08  1663.4  640.49  1692.5  653.32  1711.8  659.85
#Mann= 3 , 0 , 0
       0      .1       0   342.9    .045       0   391.9      .1       0
Bank Sta=342.9,391.9
XS Rating Curve= 0 ,0
Exp/Cntr=0.3,0.1

Chan Stop Cuts=-1
Use User Specified Reach Order=0
Composite Channel Slope=5